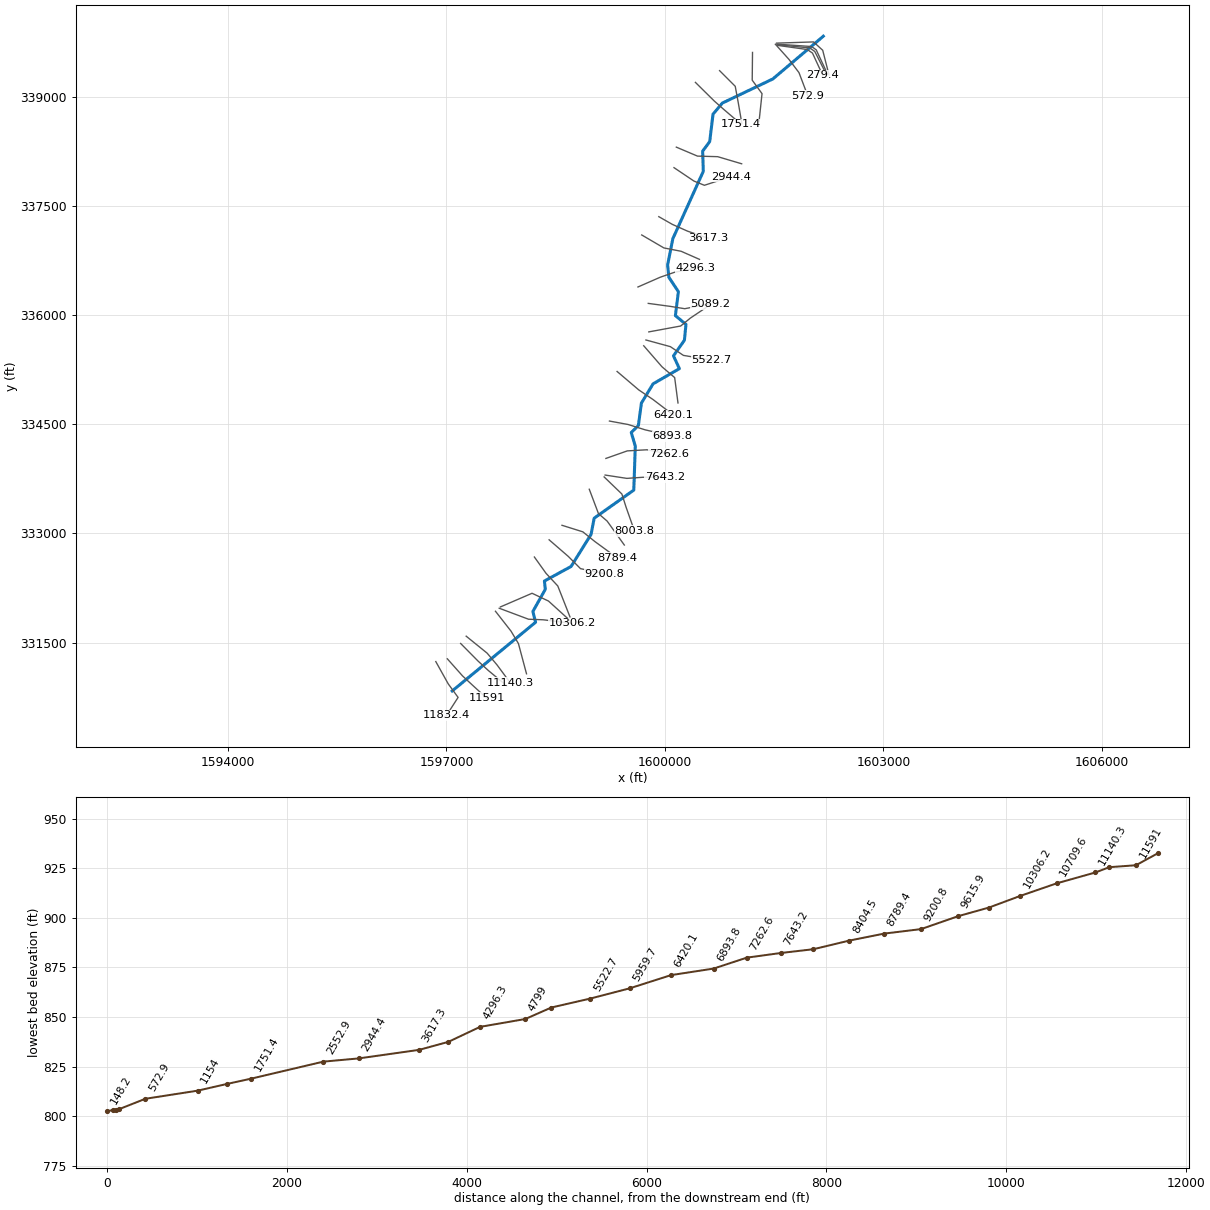
--- brdncrk.prj (project) ---

Proj Title=brdncrk
Current Plan=p01
Default Exp/Contr=0,0
English Units
Geom File=g01
Flow File=f01
Plan File=p01
BEGIN DESCRIPTION:
END DESCRIPTION:
DSS Export Rating Curves= 0
DSS Export Rating Curve Sorted= 0
DSS Export Volume Flow Curves= 0
DXF OffsetX= 0
DXF OffsetY= 0
DXF ScaleX= 0
DXF ScaleY= 0

--- brdncrk.p01 (plan) ---

Plan Title=Approximate Study - 100 yr
Program Version=4.00
Short Identifier=100 yr
Geom File=g01
Flow File=f01
Subcritical Flow
K Sum by GR= 0
Std Step Tol= 0.01
Critical Tol= 0.01
Num of Std Step Trials= 20
Max Error Tol= 0.3
Flow Tol Ratio= 0.001
Split Flow NTrial= 30
Split Flow Tol= 0.02
Split Flow Ratio= 0.02
Log Output Level= 0
Friction Slope Method= 1
Unsteady Friction Slope Method= 2
Unsteady Bridges Friction Slope Method= 1
Parabolic Critical Depth
Global Vel Dist= 0 , 0 , 0
Global Log Level= 0
CheckData=True
Encroach Param=-1 ,0,0, 0
Run HTab= 0
Run UNet= 0
Run PostProcess= 0
Run WQNet= 0
UNET Theta= 0
UNET Theta Warmup= 0
UNET ZTol= 0
UNET ZSATol= 0
UNET MxIter= 0
UNET MaxInSteps= 0
UNET DtIC= 0
UNET DtMin= 0
UNET MaxCRTS= 0
UNET WFStab= 0
UNET SFStab= 0
UNET WFX= 1
UNET SFX= 1
UNET DSS MLevel= 1
UNET DZMax Abort= 0
UNET Convert EG Bridges= 0
UNET Use Existing IB Tables= 0
UNET Froude Reduction=False
UNET Froude Limit= 0
UNET Froude Power= 0
UNET Time Slicing=0,0, 5
Write IC File= 0
Echo Input=False
Echo Output=False
Write Detailed= 0
Detailed Automatic Start=False, 0
WQ ULTIMATE=-1
WQ Max Comp Step=1HOUR
WQ Output Interval=15MIN
WQ Output Selected Increments= 0
WQ Output face flow=0
WQ Output face velocity=0
WQ Output face area=0
WQ Output face dispersion=0
WQ Output cell volume=0
WQ Output cell surface area=0
WQ Output cell continuity=0
WQ Output face conc=0
WQ Output face dconc_dx=0
WQ Output face courant=0
WQ Output face peclet=0
WQ Output face adv mass=0
WQ Output face disp mass=0
WQ Output cell mass=0
WQ Output cell source sink temp=0
WQ Output cell source sink nsm=0
WQ Output MaxMinRange=-1
WQ Daily Max Min Mean=-1
WQ Daily Range=0
WQ Daily Time=0
WQ Create Restart=0
WQ Fixed Restart=0
WQ System Summary=False
Sorting and Armoring Iterations= 10
XS Update Threshold= 0.02
Hydraulics Update Threshold= 0.02
Energy Slope Method= 1
Volume Change Method= 0
XS Weighting Method= 0
Number of US Weighted Cross Sections= 1
Number of DS Weighted Cross Sections= 1
Upstream XS Weight=0.25
Main XS Weight=0.5
Downstream XS Weight=0.25
Number of DS XS's Weighted with US Boundary= 1
Upstream Boundary Weight= 1
Weight of XSs Associated with US Boundary= 0
Number of US XS's Weighted with DS Boundary= 1
Downstream Boundary Weight= 0.5
Weight of XSs Associated with DS Boundary= 0.5
Sediment Output Level= 4
Mass or Volume Output= 0
Output Increment Type= 1
Profile and TS Output Increment= 10
XS Output Flag= 0
XS Output Increment= 10
Disregard all LS=0
Disregard all Conn=0
Disregard all Breaches=0
Disregard all Pumps=0

--- brdncrk.f01 (steady flow) ---

Flow Title=USGS Regression Equation
Program Version=4.00
Number of Profiles= 1
Profile Names=P100yr
River Rch & RM=brdncrk,Main            ,11832.4
     277
River Rch & RM=brdncrk,Main            ,11591
     381
River Rch & RM=brdncrk,Main            ,9615.9
     417
River Rch & RM=brdncrk,Main            ,9200.8
     477
River Rch & RM=brdncrk,Main            ,8003.8
     515
River Rch & RM=brdncrk,Main            ,5959.7
     568
River Rch & RM=brdncrk,Main            ,3943
     626
River Rch & RM=brdncrk,Main            ,3617.3
     721
River Rch & RM=brdncrk,Main            ,2552.9
     755
River Rch & RM=brdncrk,Main            ,1751.4
     816
River Rch & RM=brdncrk,Main            ,279.4
     848
Boundary for River Rch & Prof#=brdncrk,Main            , 1
Up Type= 0
Dn Type= 3
Dn Slope=0.007111
DSS Import GetInterval= 0
DSS Import GetPeak= 0
DSS Import FillOption= 0

--- brdncrk.g01 (geometry) ---

Geom Title=USGS 3m DEM
Program Version=4.00

River Reach=brdncrk         ,Main
Reach XY= 30
     1597078.147      330836.856     1598223.395      331780.529
     1598186.357      331928.291     1598357.221      332233.486
     1598344.516      332346.479     1598710.983      332546.653
     1598985.234      332986.988     1599027.922      333209.468
      1599572.08      333595.471     1599592.665      334198.845
     1599537.254      334386.278     1599634.853      334481.759
      1599676.74      334790.391     1599836.895      335054.535
      1600198.01      335262.922     1600117.057      335439.185
     1600266.936      335653.109       1600288.5      335870.327
     1600143.184      335991.007     1600184.676      336319.631
     1600053.575      336518.051     1600036.405      336686.414
      1600108.32      337047.806     1600526.456      337972.423
     1600517.906      338249.945     1600614.391      338380.481
     1600660.084      338758.131     1600788.373      338910.184
     1601481.008      339240.827     1602174.587      339827.815

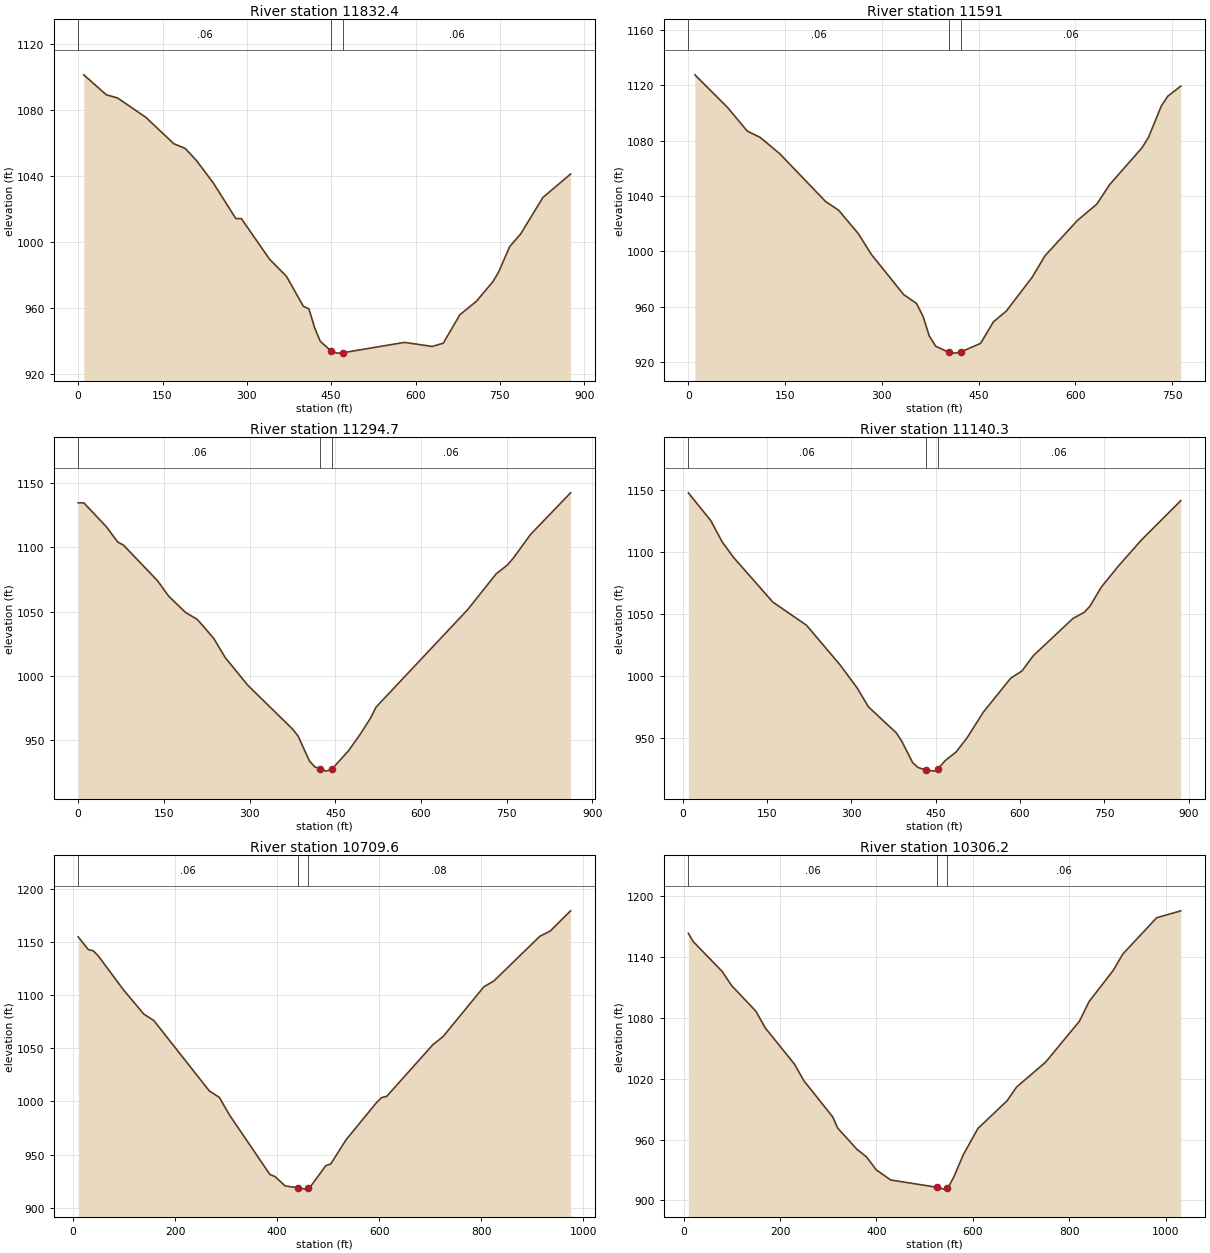
Type RM Length L Ch R = 1 ,11832.4 ,237.6,241.4,245.3
XS GIS Cut Line= 4
      1596853.16      331240.435     1597023.884      330934.461
     1597159.248      330748.562     1596999.351       330500.34
#Sta/Elev= 30
      10 1101.12    50.1 1089.02    70.1 1087.11   120.1 1075.45   170.2 1059.38
   190.2 1056.59   210.2  1049.3   240.3 1035.65   280.3 1014.12   290.3 1014.03
   340.4  989.44   370.4  979.11   400.4  960.98   410.4  959.39   420.4  948.06
   430.4  939.82   450.4   933.7   460.4   932.6   470.4  932.82   580.3  939.11
   629.6  936.65   649.2   938.6   678.8  955.85   708.3  964.04   737.8  976.03
   747.7  981.73   767.3  997.06     787 1004.82   826.4 1026.86   875.6 1041.03
#Mann= 3 , 0 , 0
       0     .06       0   450.4    .045       0   470.4     .06       0
Bank Sta=450.4,470.4
XS Rating Curve= 0 ,0
Exp/Cntr=0.3,0.1

Type RM Length L Ch R = 1 ,11591   ,296.2,296.3,296.4
XS GIS Cut Line= 4
     1597011.534      331278.506     1597220.161       331043.99
     1597351.125      330922.164     1597550.615      330739.425
#Sta/Elev= 30
    10.1 1127.43    60.8 1103.85    91.1 1086.91   111.4 1082.24   141.8 1070.42
   212.6 1036.07   232.9 1029.74   263.3 1012.91   283.5  997.95   333.8  968.81
   353.6  962.51   363.6  953.33   373.5  938.93   383.4  931.59   403.3  927.28
   413.3  926.62   423.3  927.65     453  933.68   472.9  949.23   492.7  956.91
   532.8  981.29   552.9  996.94     603 1022.32     633 1034.08   653.1 1048.25
   703.2  1074.8   713.2 1082.29   733.2 1105.06   743.2 1112.02   763.3  1119.3
#Mann= 3 , 0 , 0
       0     .06       0   403.3    .045       0   423.3     .06       0
Bank Sta=403.3,423.3
XS Rating Curve= 0 ,0
Exp/Cntr=0.3,0.1

Type RM Length L Ch R = 1 ,11294.7 ,157.1,154.4,151.7
XS GIS Cut Line= 4
     1597194.391      331489.118     1597431.017      331249.934
     1597574.272       331118.19     1597828.806      330907.145
#Sta/Elev= 30
       0  1134.7     9.9  1134.7    49.5 1115.99    69.3 1104.12    79.2 1101.79
   138.5 1074.23   158.3 1062.03     188 1049.25   207.8 1044.07   217.7 1039.27
   237.5 1028.88   257.3 1014.18   296.9  992.53   375.4  958.33   385.1  952.83
   404.6   933.6   414.3  928.85   423.8  927.57   433.8  925.64   443.8  927.09
   472.7  941.28   492.2  953.45   511.6  966.89   521.3  975.51   681.4 1051.36
   731.5 1079.37   751.5 1086.39   761.5 1091.62   791.6 1110.04   861.7  1142.5
#Mann= 3 , 0 , 0
       0     .06       0   423.8    .045       0   443.8     .06       0
Bank Sta=423.8,443.8
XS Rating Curve= 0 ,0
Exp/Cntr=0.3,0.1

Type RM Length L Ch R = 1 ,11140.3 ,433.8,430.7,427.6
XS GIS Cut Line= 4
     1597270.414      331589.163     1597558.229       331356.17
     1597695.284      331193.227     1597874.977      330949.575
#Sta/Elev= 30
      10 1148.08      50 1125.51    70.1 1108.42    90.1 1095.97   160.1 1059.76
   220.2 1040.94   280.2  1008.7   310.3   990.2   330.3  974.99     380  953.86
   389.7  947.12     409  929.81   418.7  925.87  432.88  923.86   447.7  922.97
  453.32  924.52   467.1  931.58   486.4  938.52   505.8  949.93   534.8  970.71
   583.2  998.06   603.4 1003.93   623.6 1016.34   694.2 1046.48   714.4 1051.47
   724.5 1056.46   744.7 1071.89     775 1088.85   815.3  1109.6     886 1141.78
#Mann= 3 , 0 , 0
      10     .06       0  432.88    .045       0  453.32     .06       0
Bank Sta=432.88,453.32
XS Rating Curve= 0 ,0
Exp/Cntr=0.3,0.1

Type RM Length L Ch R = 1 ,10709.6 ,383.3,403.4,423.5
XS GIS Cut Line= 4
     1597672.441      331931.799     1597885.637      331659.213
     1597987.667      331488.656     1598098.833      331072.924
#Sta/Elev= 30
     9.9 1155.07    29.7 1143.14    39.5  1141.9    49.4 1137.04    98.9 1105.05
   138.4 1082.41   158.2 1076.25     267 1009.95   286.7 1003.85   306.5   987.3
   385.8  931.22   395.7  929.33   415.6  920.51  441.64  918.74   455.4  917.48
  459.91  918.61   465.3  919.91   495.1  939.43   505.1  941.22   534.9  963.86
   594.8  999.03   604.8 1003.68   614.9 1004.94   704.9 1053.32   724.9 1060.99
     805 1107.92     825  1113.6   915.1 1155.67   935.1 1160.46   975.1 1179.54
#Mann= 3 , 0 , 0
     9.9     .06       0  441.64    .045       0  459.91     .08       0
Bank Sta=441.64,459.91
XS Rating Curve= 0 ,0
Exp/Cntr=0.3,0.1

Type RM Length L Ch R = 1 ,10306.2 ,357.7,349.8,341.9
XS GIS Cut Line= 4
     1597724.217      331972.916     1598126.244      331822.156
     1598327.257      331814.541     1598724.716      331765.811
#Sta/Elev= 30
      10 1163.48      20 1155.37    79.9 1125.95    99.9 1111.79   149.8  1086.8
   169.7 1069.98   229.7 1034.65   249.6 1018.02   309.5  982.27   319.5  971.41
   359.5  950.46   379.4  942.92   399.4  930.24   429.4  920.19  525.38  912.99
     540  911.16  545.74  912.68   550.1  914.07   560.1  922.93   580.2  945.24
   610.4  971.05   670.6  998.17   690.6 1011.89   750.7 1036.41   820.7  1076.7
   840.8 1096.15   890.8 1126.84   910.8 1143.05   980.9 1178.83    1031 1185.68
#Mann= 3 , 0 , 0
      10     .06       0  525.38    .045       0  545.74     .06       0
Bank Sta=525.38,545.74
XS Rating Curve= 0 ,0
Exp/Cntr=0.3,0.1

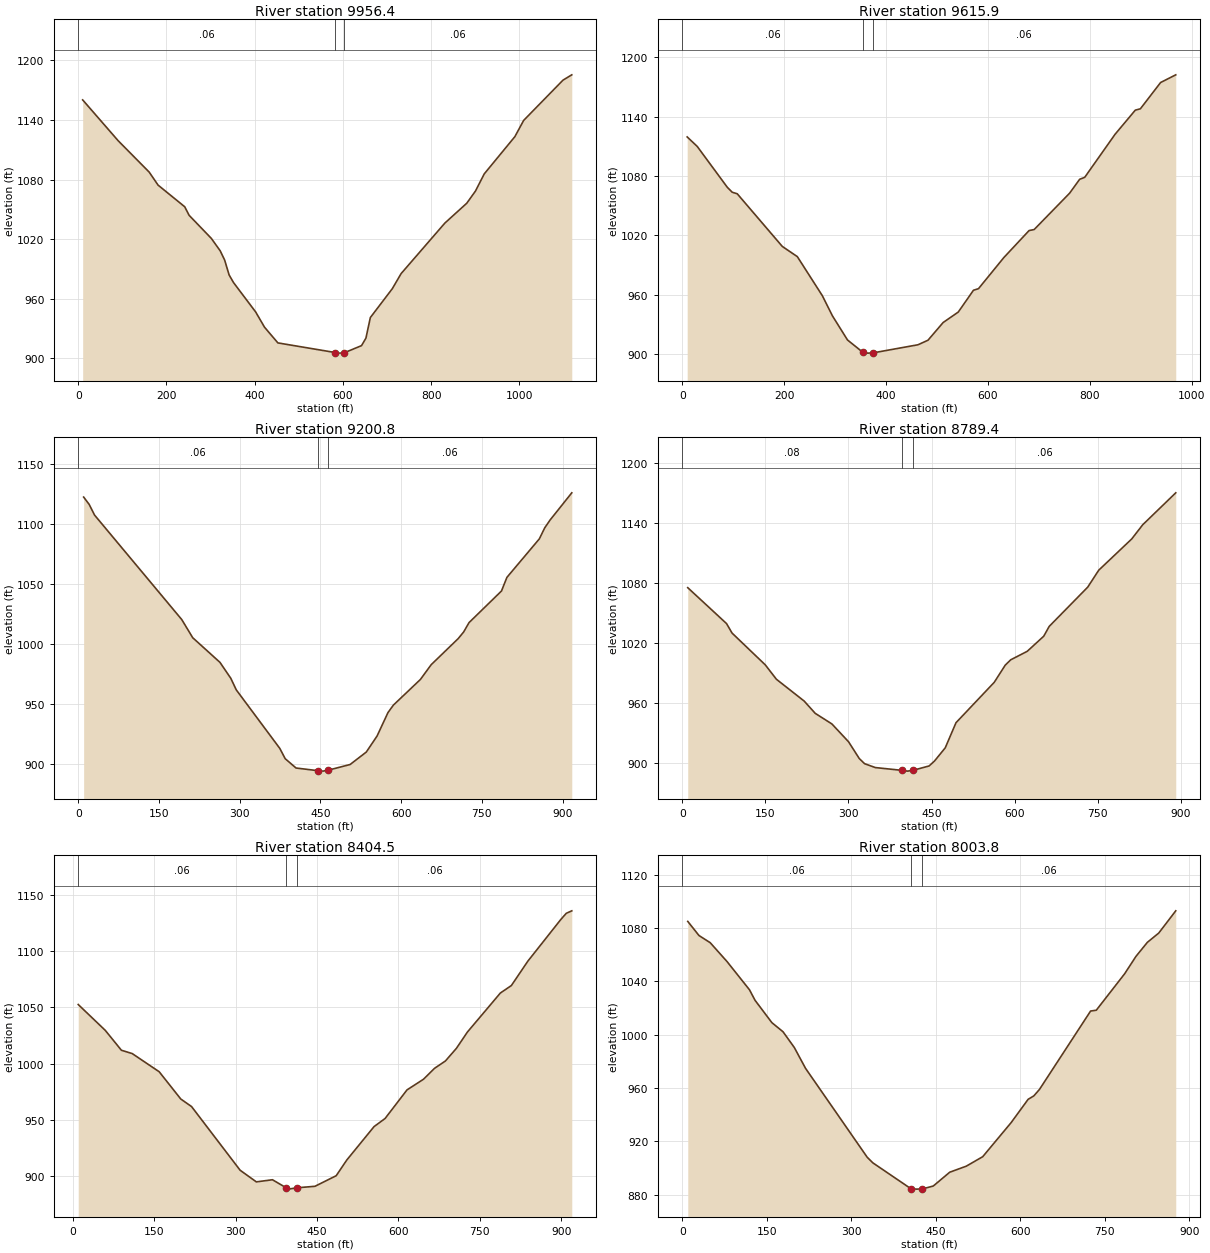
Type RM Length L Ch R = 1 ,9956.4  ,349.3,340.4,330.6
XS GIS Cut Line= 4
     1597740.968      331991.189     1598174.975      332178.497
     1598400.353      332071.899     1598694.259      331805.404
#Sta/Elev= 30
    10.1  1160.2    90.5 1119.13   160.9 1087.49     181 1074.42   241.4 1052.63
   251.4    1044   301.7 1020.78   321.8 1008.29   331.9     999     342  984.04
     352  976.32   402.3  946.66   422.4  931.32   452.6  915.55   582.4  905.87
   592.4  905.26   602.4  905.49   642.2   912.8   652.2  920.37   662.2  941.07
     712  970.14   731.9   985.3   831.1 1036.18   880.7 1056.14   900.5 1068.44
   920.4 1085.73   989.8 1123.19  1009.7 1139.53  1098.9 1180.09  1118.8 1185.44
#Mann= 3 , 0 , 0
       0     .06       0   582.4    .045       0   602.4     .06       0
Bank Sta=582.4,602.4
XS Rating Curve= 0 ,0
Exp/Cntr=0.3,0.1

Type RM Length L Ch R = 1 ,9615.9  ,414.4,415.1,415.6
XS GIS Cut Line= 4
     1598206.954      332676.462     1598366.851      332452.607
     1598528.271      332279.004     1598695.782      331854.135
#Sta/Elev= 30
     9.8  1119.6    29.5 1110.02    88.4 1068.77    98.2 1063.67   108.1 1062.09
   196.5 1008.85     226  998.53   275.1  959.02   294.9  938.64   324.5  914.23
     354  902.01     364  900.93     374  901.13   462.8  909.38   482.5  913.99
   512.2  931.88   541.9  942.46   571.7  964.51   581.6  966.12   631.3  997.55
   680.9  1024.9   690.9 1025.94   760.4 1062.67   780.2 1076.77   790.1 1078.74
   849.7 1122.29   889.4 1146.69   899.4 1148.07   939.1 1174.65   968.8 1182.42
#Mann= 3 , 0 , 0
       0     .06       0     354    .045       0     374     .06       0
Bank Sta=354,374
XS Rating Curve= 0 ,0
Exp/Cntr=0.3,0.1

Type RM Length L Ch R = 1 ,9200.8  ,409.4,411.4,413.4
XS GIS Cut Line= 4
      1598409.49      332912.501     1598669.894      332687.122
     1598840.451      332516.565     1599164.813      332448.038
#Sta/Elev= 30
    10.1  1122.3    20.3 1116.25    30.4 1107.31   192.5 1020.37   212.7 1005.36
   263.4  984.83   283.6  971.52   293.7  961.96   374.5  913.33   384.6  904.72
   404.7  896.98   444.9  894.77   454.9  894.38   464.9  895.21   505.2  899.88
   535.3  910.25   555.4  923.65   575.5  943.01   585.6  949.27   635.8   970.6
   655.9  982.92   706.1 1004.61   716.2 1010.13   726.2  1017.9   786.5  1044.2
   796.6 1055.54   856.8 1087.53   866.9 1096.76   876.9 1103.29   917.1 1125.84
#Mann= 3 , 0 , 0
       0     .06       0   444.9    .045       0   464.9     .06       0
Bank Sta=444.9,464.9
XS Rating Curve= 0 ,0
Exp/Cntr=0.3,0.1

Type RM Length L Ch R = 1 ,8789.4  ,385.4,384.9,384.5
XS GIS Cut Line= 4
     1598586.138      333111.991      1598872.43      333022.144
     1599038.418      332888.136     1599342.984      332665.802
#Sta/Elev= 30
      10 1075.57      80 1039.67      90 1030.15     150  998.32     170  983.97
     220  962.21     240   949.9   270.1  939.29   300.1  921.51   319.5  904.69
   329.1  899.53   348.5  895.66   396.7  892.86   406.7   892.1   416.7  892.94
   445.5  897.28   455.2   902.2   474.6  915.39     494  940.51     563  980.91
   582.9  998.12   592.8 1003.45   622.5  1011.9   652.3 1027.03   662.2 1036.85
   731.7 1076.11   751.5 1093.01   811.1 1124.32   830.9 1138.48   890.5 1170.42
#Mann= 3 , 0 , 0
       0     .08       0   396.7    .045       0   416.7     .06       0
Bank Sta=396.7,416.7
XS Rating Curve= 0 ,0
Exp/Cntr=0.3,0.1

Type RM Length L Ch R = 1 ,8404.5  ,411.8,400.7,389.6
XS GIS Cut Line= 4
     1598960.754       333606.91     1599087.149      333271.888
      1599205.93      333169.859     1599441.968      332840.928
#Sta/Elev= 30
     9.9 1052.63    59.7 1029.69    89.5 1011.98   109.4 1009.04   159.1   992.9
   198.9  968.67   218.8  961.94   308.3  905.38   338.2  895.04   367.9  896.94
  392.65  889.95   397.2   888.6  412.89  889.77   446.2  891.12   485.3  900.49
   504.9  914.49   555.1  944.14   575.4  951.33   615.9  976.79   646.2  986.22
   666.5   995.9   686.7 1002.49     707 1013.75   727.2 1028.18   787.9 1062.83
   808.2 1069.49   838.5 1091.11   899.3 1128.17   909.4 1133.67   919.5 1135.86
#Mann= 3 , 0 , 0
     9.9     .06       0  392.65    .045       0  412.89     .06       0
Bank Sta=392.65,412.89
XS Rating Curve= 0 ,0
Exp/Cntr=0.3,0.1

Type RM Length L Ch R = 1 ,8003.8  ,333.7,360.5,387.4
XS GIS Cut Line= 4
     1599164.813      333775.944     1599408.466      333541.429
     1599467.856      333355.644     1599582.068      333032.804
#Sta/Elev= 30
     9.9 1084.89    29.8 1074.32    49.7 1068.95    79.6 1054.79   119.4 1033.64
   129.3 1025.74   159.1 1009.03     179 1002.14   198.9   990.4   218.8  974.79
   328.2  908.16   338.2  903.95   406.2  884.44   416.2  884.23   426.2  884.38
   445.5  886.56   474.7  896.91     504  901.43   533.2  908.53   583.6  934.07
   613.8  951.55   623.9  954.13   633.9  958.95   724.6 1017.71   734.7 1018.33
     785 1045.64   805.2 1058.74   825.3 1069.19   845.5 1076.15   875.7 1092.83
#Mann= 3 , 0 , 0
       0     .06       0   406.2    .045       0   426.2     .06       0
Bank Sta=406.2,426.2
XS Rating Curve= 0 ,0
Exp/Cntr=0.3,0.1

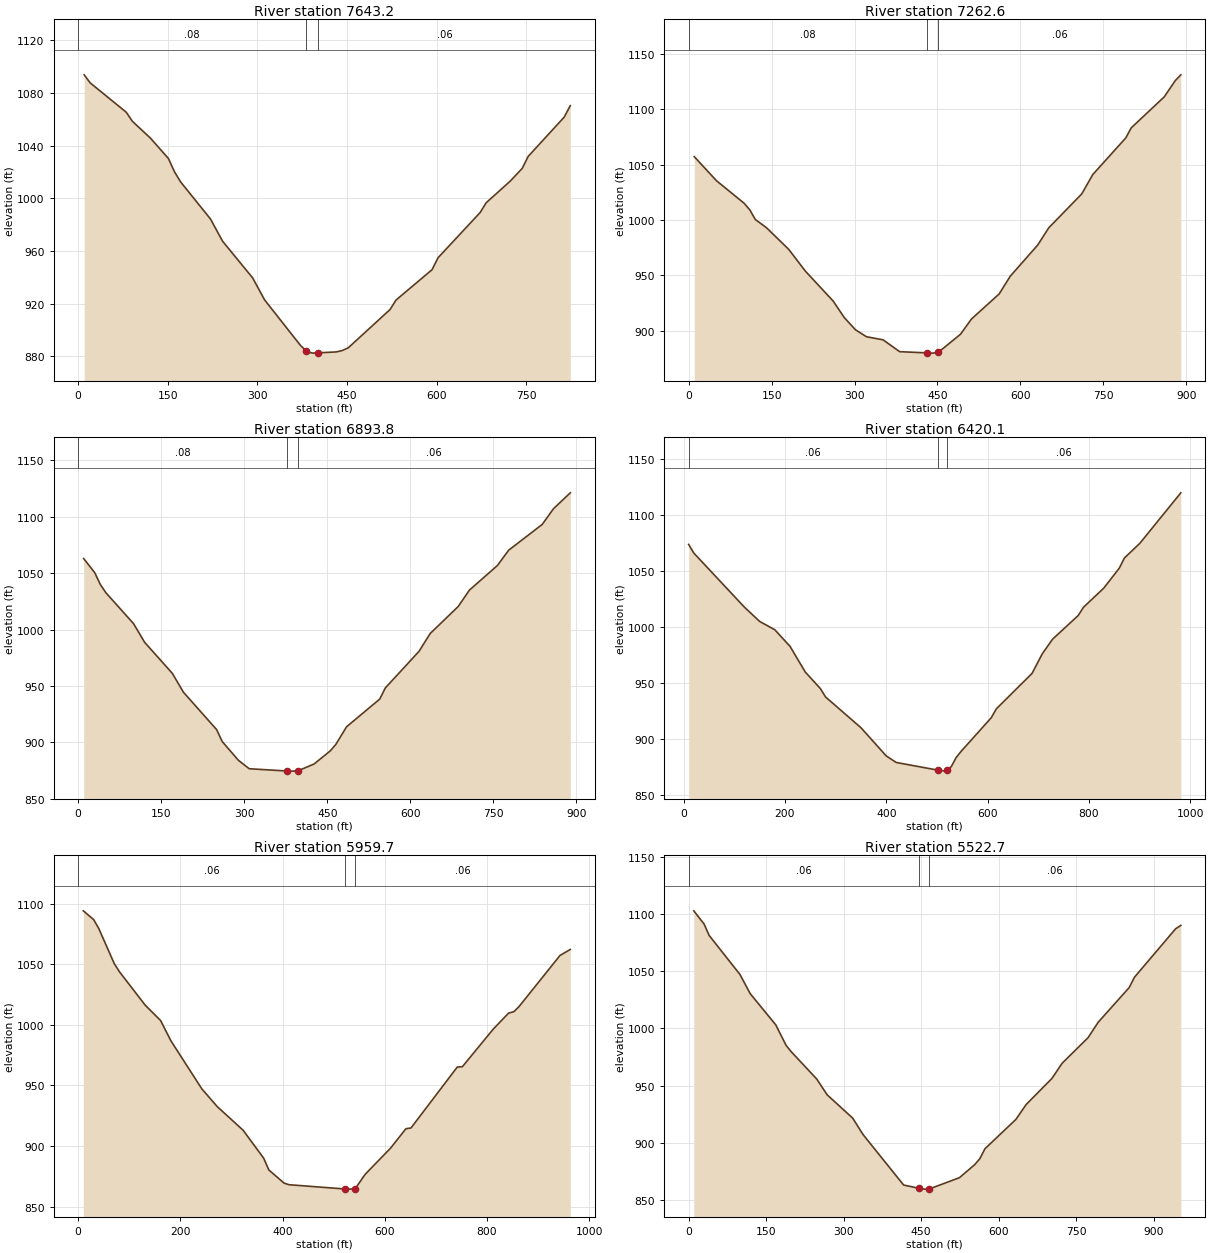
Type RM Length L Ch R = 1 ,7643.2  ,380.4,380.6,380.9
XS GIS Cut Line= 4
     1599178.519      333801.833     1599476.993      333756.148
      1599696.28      333771.376       1599997.8      333774.422
#Sta/Elev= 30
    10.1 1093.85    20.1 1087.76    80.5 1065.42    90.6 1058.59   120.8 1045.81
     151 1030.26     161 1020.33   171.1 1012.65   221.4  984.28   241.6   967.4
   291.9  939.53   311.9  922.81   371.9  888.22   381.9   883.8   391.9  882.33
   401.9  882.56   431.8  883.25   441.8  884.29   451.8  886.34   521.8  915.48
   531.8  922.68   592.1  945.76   602.2  954.88   672.5  989.19   682.6  996.62
   722.8 1013.05   742.9 1022.73   752.9 1031.86   813.2 1061.74   823.3 1070.44
#Mann= 3 , 0 , 0
       0     .08       0   381.9    .045       0   401.9     .06       0
Bank Sta=381.9,401.9
XS Rating Curve= 0 ,0
Exp/Cntr=0.3,0.1

Type RM Length L Ch R = 1 ,7262.6  ,373.8,368.8,361.3
XS GIS Cut Line= 4
     1599189.178      334030.257     1599483.084      334133.809
     1599752.625      334149.038     1600055.668       334091.17
#Sta/Elev= 30
    10.1 1057.14    50.3 1035.44   100.5 1015.02   110.6 1009.12   120.6 1000.43
   140.7  993.07   180.9  973.58   211.1   953.9   261.4  926.89   281.5  911.99
   301.6  901.06   321.6  894.73   351.6  891.98   381.6  881.28   431.6  880.18
   441.6  879.97   451.6  880.73   491.6  896.97   511.6   910.8   561.6  933.35
   581.6  949.31   631.3  977.43   651.3  992.99     711 1023.57   730.9 1041.01
   790.6 1074.04   800.5 1083.11   860.2 1111.09   880.2 1125.76   890.1 1130.92
#Mann= 3 , 0 , 0
       0     .08       0   431.6    .045       0   451.6     .06       0
Bank Sta=431.6,451.6
XS Rating Curve= 0 ,0
Exp/Cntr=0.3,0.1

Type RM Length L Ch R = 1 ,6893.8  ,483,473.7,466.9
XS GIS Cut Line= 4
     1599237.909       334543.45     1599493.744      334496.242
     1599726.737      334423.147     1600101.353      334336.345
#Sta/Elev= 30
      10 1062.92      30 1050.37      40 1039.99      50 1032.67   100.1  1005.2
   120.1  988.65   170.1  961.15   190.1  944.45   250.1  911.28   260.2  900.71
   289.5  884.05     309  876.57   377.1  874.56   387.1  874.45   397.1  874.73
   426.2  880.78   455.5  892.44   465.3  898.02   484.8  913.75   544.8  938.34
   554.9  948.24   615.7  980.66   635.9  996.49   686.5 1020.42   706.7 1034.92
   757.3 1056.76   777.6  1070.3   838.3 1093.21   858.5 1107.07   888.9 1121.19
#Mann= 3 , 0 , 0
       0     .08       0   377.1    .045       0   397.1     .06       0
Bank Sta=377.1,397.1
XS Rating Curve= 0 ,0
Exp/Cntr=0.3,0.1

Type RM Length L Ch R = 1 ,6420.1  ,462,460.4,458.7
XS GIS Cut Line= 4
     1599342.984      335224.154     1599639.936      334971.365
      1599836.38      334838.879     1600118.104       334624.16
#Sta/Elev= 30
      10 1073.53      20 1065.87     120 1017.51     150  1004.8     180  997.33
     210  982.52     240  959.66     270  944.76     280  937.39     350  909.88
   399.9   884.7   419.6  878.88  501.73  872.04   518.3  871.15  519.93  871.82
   528.2  875.21   538.1  883.48   547.9  888.94   607.2  918.89   617.1  926.75
   687.6   958.4   707.9  975.98   728.1  988.93   778.7 1010.08   788.9 1017.33
   829.3  1034.6   859.7 1052.33   869.8 1061.36   900.2 1074.45   981.1 1119.56
#Mann= 3 , 0 , 0
      10     .06       0  501.73    .045       0  519.93     .06       0
Bank Sta=501.73,519.93
XS Rating Curve= 0 ,0
Exp/Cntr=0.3,0.1

Type RM Length L Ch R = 1 ,5959.7  ,431.2,437,441
XS GIS Cut Line= 4
     1599708.463      335577.451      1599959.73      335288.113
     1600133.332      335140.399     1600179.017      334791.671
#Sta/Elev= 30
    10.1    1094    30.3  1086.8    40.3 1079.46    70.6 1050.52    80.7 1043.82
   131.1 1016.24   161.4 1003.49   181.5  986.79     242  947.18   272.3  932.47
   322.7  913.07     363  890.01   373.1   880.3     403   869.4   412.9  868.09
   521.9  864.59   531.9  864.47   541.9  864.72   561.6   876.7   611.2  898.25
   641.3  914.28   651.3  914.93   741.8  965.17   751.8  965.45   812.1  996.41
   842.3 1009.69   852.3 1010.74   862.4 1014.92   942.8  1057.2   962.9 1062.15
#Mann= 3 , 0 , 0
       0     .06       0   521.9    .045       0   541.9     .06       0
Bank Sta=521.9,541.9
XS Rating Curve= 0 ,0
Exp/Cntr=0.3,0.1

Type RM Length L Ch R = 1 ,5522.7  ,407.2,433.5,459.8
XS GIS Cut Line= 4
     1599738.919      335656.638     1600073.942      335565.268
     1600253.636      335444.965     1600637.388      335381.006
#Sta/Elev= 30
     9.9 1102.88    29.8 1091.34    39.7 1081.31    99.2 1047.24   119.1 1030.41
   168.7 1003.03   188.5  985.17   198.4  979.65     248  955.63   267.9  941.93
   317.5  921.45   337.3  907.22   416.1  862.89   445.4  860.11   455.4  859.32
   465.4   859.4   524.2  869.36   553.7  880.77   563.5  885.92   573.5  894.65
   633.3   920.3   653.3  933.38   703.2  956.23   723.1  969.59     773  991.81
   792.9 1005.48   852.8 1035.78   862.8 1044.72   942.6 1087.19   952.6 1090.11
#Mann= 3 , 0 , 0
       0     .06       0   445.4    .045       0   465.4     .06       0
Bank Sta=445.4,465.4
XS Rating Curve= 0 ,0
Exp/Cntr=0.3,0.1

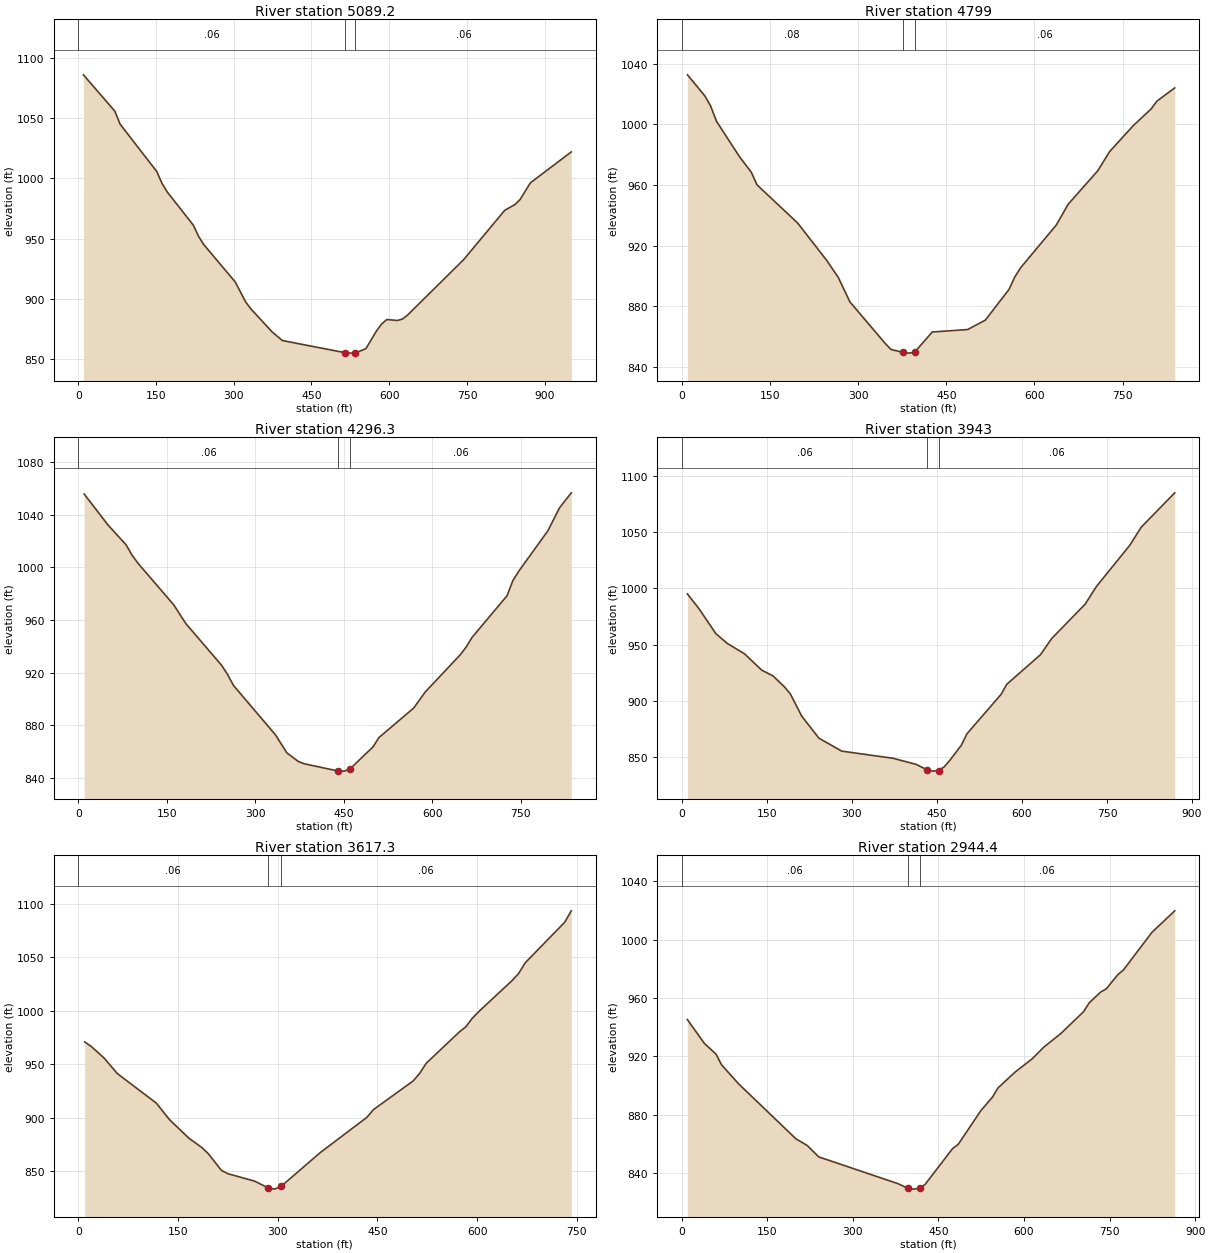
Type RM Length L Ch R = 1 ,5089.2  ,308,290.3,272.5
XS GIS Cut Line= 4
     1599778.513      335767.804     1600215.565      335848.514
     1600348.051      335956.635     1600626.728      336143.943
#Sta/Elev= 30
    10.1 1085.94    70.7 1055.75    80.8 1045.03   151.5 1005.66   161.6  995.86
   171.7   988.7   222.2  961.01   232.3   951.7   242.4  944.88     303  913.89
   323.2  897.19   333.3  891.49   373.7  872.59   393.9  865.26   514.9  855.15
   524.9   854.8   534.9  854.96   555.1  858.57   575.2  873.07   585.3  878.97
   595.3  882.71   615.4  881.93   625.3  883.05   635.2  886.34   743.8  932.55
   822.8  973.41   842.6  978.25   852.5   982.4   872.2   996.2   951.2 1021.93
#Mann= 3 , 0 , 0
       0     .06       0   514.9    .045       0   534.9     .06       0
Bank Sta=514.9,534.9
XS Rating Curve= 0 ,0
Exp/Cntr=0.3,0.1

Type RM Length L Ch R = 1 ,4799    ,492.5,502.6,512.8
XS GIS Cut Line= 4
     1599770.899      336159.171     1600073.942      336118.055
     1600271.909      336086.075     1600597.795      336150.034
#Sta/Elev= 30
     9.9  1032.7    39.5 1018.77    49.3  1012.1    59.2 1002.07    98.7  978.47
   118.4  968.42   128.2  960.05   197.3  934.86   246.6  910.23   266.4  898.95
   286.1  882.82   345.9   855.5     356  851.38     376  849.52     386  848.98
     396  849.49   426.1  862.92   486.3  864.55   516.4  870.75   556.7  891.04
   566.7  899.39   576.8  905.53   637.2   933.6   657.3  947.28   707.6  969.35
   727.8  982.03     768  999.17   798.2 1010.12   808.3 1015.37   838.5 1024.08
#Mann= 3 , 0 , 0
       0     .08       0     376    .045       0     396     .06       0
Bank Sta=376,396
XS Rating Curve= 0 ,0
Exp/Cntr=0.3,0.1

Type RM Length L Ch R = 1 ,4296.3  ,363.9,353.3,342.7
XS GIS Cut Line= 4
     1599629.276       336384.55     1599935.364      336518.559
     1600128.764      336585.563     1600419.624      336644.953
#Sta/Elev= 30
    10.1 1055.76    50.6 1032.18      81 1017.24    91.1 1009.43   101.3 1003.14
     162  971.45   182.3  957.31     243  925.54   253.1  918.58   263.3  910.12
   334.1  872.77   353.6  858.96   373.1  852.36   382.9  850.63   441.1  845.06
   451.1  845.03   461.1  846.88   499.8  863.52   509.6  870.52   568.5  892.94
   588.3  905.27   647.7   933.6   657.6  939.43   667.5  946.72   726.8  978.39
   736.7  989.93   746.6  997.01   796.1 1027.83   815.9 1045.38   835.7 1056.67
#Mann= 3 , 0 , 0
       0     .06       0   441.1    .045       0   461.1     .06       0
Bank Sta=441.1,461.1
XS Rating Curve= 0 ,0
Exp/Cntr=0.3,0.1

Type RM Length L Ch R = 1 ,3943    ,330.2,325.7,321.2
XS GIS Cut Line= 4
     1599681.052      337098.756     1599985.618      336920.585
     1600221.656        336874.9     1600474.446      336763.734
#Sta/Elev= 30
    10.1  995.05    30.2  982.12    60.5  959.58    80.7  950.93   110.9  941.73
   141.1  927.27   161.3  922.04   181.5  912.25   191.5  906.22   211.7  886.37
     242  866.77   282.3  855.23   372.9  848.86     413  843.54     433  838.61
     443  837.45     453  837.98     463  841.24   473.1   847.2   493.1  860.44
   503.1   870.7   563.2  905.68   573.2  914.64   632.7  940.97   652.4  955.31
   711.6  985.99   731.3 1001.62   790.5 1038.47   810.2 1054.28   869.4 1084.89
#Mann= 3 , 0 , 0
       0     .06       0     433    .045       0     453     .06       0
Bank Sta=433,453
XS Rating Curve= 0 ,0
Exp/Cntr=0.3,0.1

Type RM Length L Ch R = 1 ,3617.3  ,672.2,672.9,673.6
XS GIS Cut Line= 4
     1599915.568      337350.023     1600102.875      337243.425
     1600311.503      337150.532     1600593.226      337054.594
#Sta/Elev= 30
     9.8  970.99    19.6  966.81    39.2   955.8    58.8  941.46   117.6  913.76
   137.1  898.49   166.5  881.03   186.1  872.23   195.9  866.39   215.5  850.84
   225.4  847.78   265.2   840.9     285  834.76     295  833.41     305  835.93
   364.5  867.81     434  900.43   443.9  907.68   503.4  934.39   513.3  941.41
   523.3  951.02   572.9  980.19   582.8  985.07   592.7  993.15   602.6   999.5
   652.2 1028.18   662.1 1034.79   672.1 1044.89   731.6 1082.87   741.5 1093.55
#Mann= 3 , 0 , 0
       0     .06       0     285    .045       0     305     .06       0
Bank Sta=285,305
XS Rating Curve= 0 ,0
Exp/Cntr=0.3,0.1

Type RM Length L Ch R = 1 ,2944.4  ,383.9,391.5,399.1
XS GIS Cut Line= 4
     1600124.195      338023.113     1600398.304      337838.851
      1600541.45      337780.983     1600902.361      337898.241
#Sta/Elev= 30
      10  945.25      40  928.83    60.1  921.66    70.1  914.15   100.1   901.1
   200.2  863.58   220.2  858.96   240.2  851.18   378.5  832.92   397.5  829.55
   407.5  829.09   417.5  829.75   426.8   832.4     475  856.93   484.7  859.73
   524.6  882.98   544.6  892.03   554.6  898.47   584.5  909.29   614.5  918.41
   634.5  926.28   664.4  935.62   704.4  950.64   714.4  956.74   734.3  964.09
   744.3  966.29   764.3  975.91   774.3  979.23   824.2 1004.97   864.2 1019.73
#Mann= 3 , 0 , 0
       0     .06       0   397.5    .045       0   417.5     .06       0
Bank Sta=397.5,417.5
XS Rating Curve= 0 ,0
Exp/Cntr=0.3,0.1

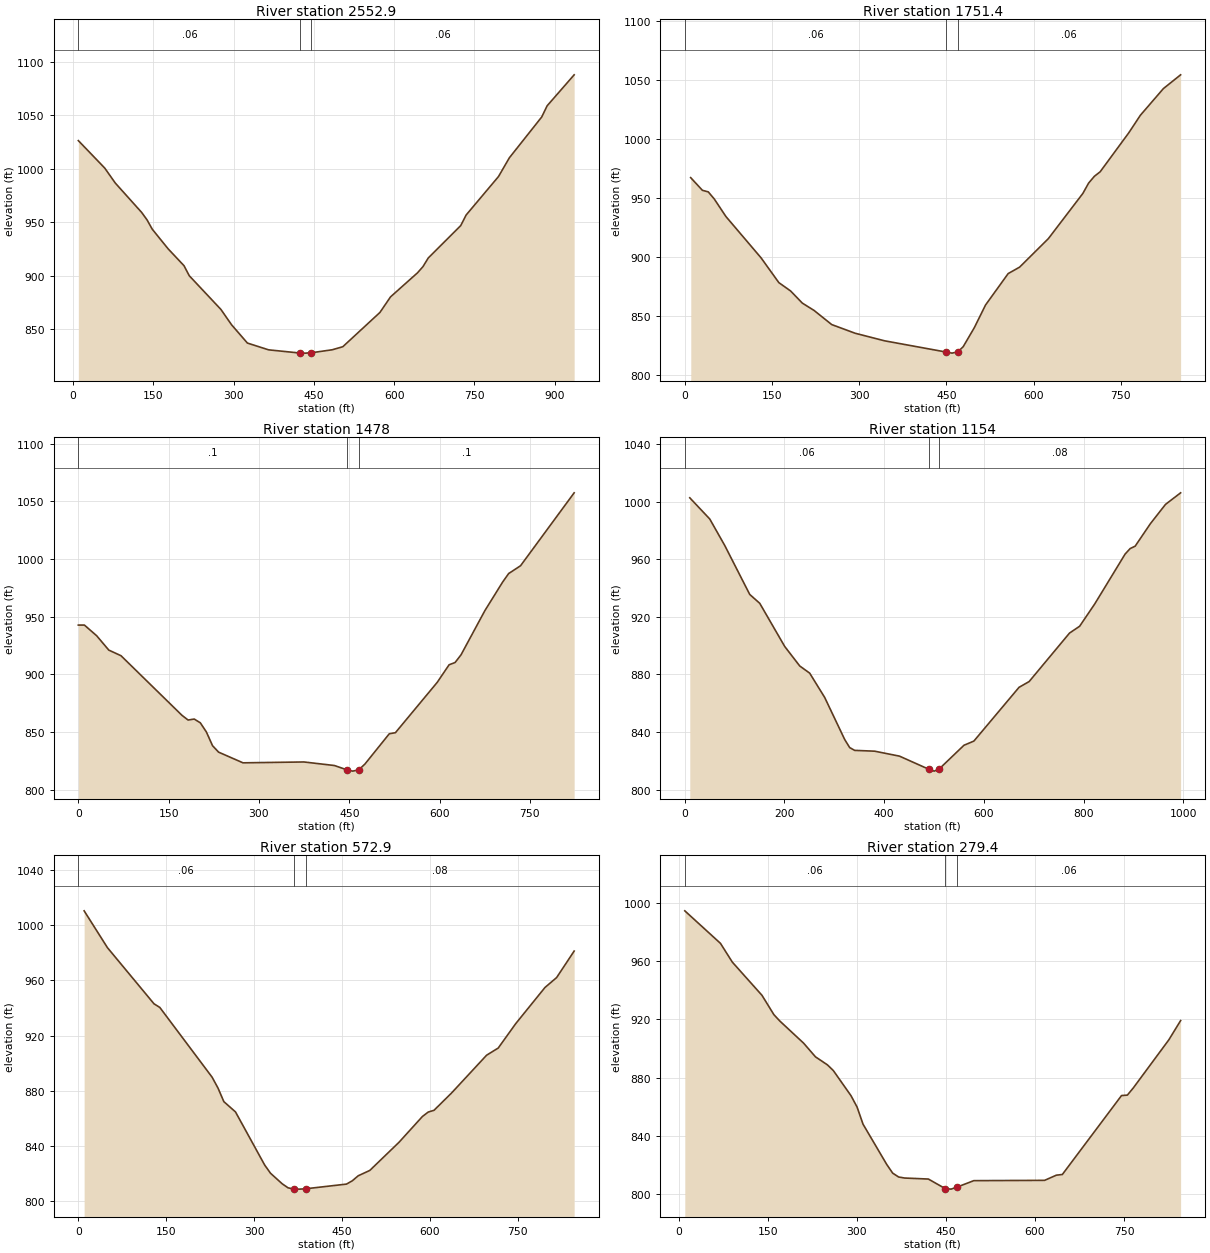
Type RM Length L Ch R = 1 ,2552.9  ,815.8,801.4,787.1
XS GIS Cut Line= 4
     1600156.174      338304.836     1600447.035      338181.487
      1600724.19      338173.873     1601053.121      338076.412
#Sta/Elev= 30
     9.9 1026.43    59.2 1000.74      79  986.67   128.3  959.14   138.2  952.27
   148.1  943.44   177.7   925.1   207.3  909.34   217.2  899.91   276.4  868.31
   296.2  854.02   325.8  836.89   365.4  830.55   424.8   827.5  434.75  827.47
   444.8  827.78   484.3  830.61   504.1  833.49   573.4  865.55   593.2  880.12
   643.6  902.65   653.7  908.36   663.8   916.6   724.4  946.88   734.5  956.79
     795  992.82   815.2 1010.31   875.7 1048.54   885.8    1059   936.3 1088.01
#Mann= 3 , 0 , 0
     9.9     .06       0   424.8    .045       0   444.8     .06       0
Bank Sta=424.8,444.8
XS Rating Curve= 0 ,0
Exp/Cntr=0.3,0.1

Type RM Length L Ch R = 1 ,1751.4  ,286.8,273.4,260
XS GIS Cut Line= 4
     1600418.101      339194.168     1600676.982      338938.333
     1600806.422      338824.121     1601047.029      338618.539
#Sta/Elev= 30
    10.1  967.47    30.3  956.72    40.4  955.39    50.6  949.46    70.8  934.51
   131.4  899.45   161.8  878.59     182  871.54   202.2  861.25   222.4  855.04
   252.8  843.07   293.2  835.71   343.7  829.33   449.9  819.78   459.9   818.9
   469.9  820.04     479  824.34   498.2   840.5   517.4   859.6   556.4  886.24
   576.1   891.7   625.6  915.85   684.9  954.08   694.8  962.83   704.7  968.58
   714.6  972.37   764.1 1005.52   783.8 1020.21   823.4  1042.8   853.1 1054.48
#Mann= 3 , 0 , 0
       0     .06       0   449.9    .045       0   469.9     .06       0
Bank Sta=449.9,469.9
XS Rating Curve= 0 ,0
Exp/Cntr=0.3,0.1

Type RM Length L Ch R = 1 ,1478    ,315.5,324,332.6
XS GIS Cut Line= 4
     1600750.184      339355.351     1600965.066      339140.469
     1601007.275      338911.517      1601055.88      338628.844
#Sta/Elev= 30
       0  942.83    10.1  942.83    30.4  933.61    50.6  921.14    70.9  916.25
   172.2  864.54   182.3  860.49   192.5  861.33   202.6  858.08   212.7  850.12
   222.9  838.25     233  832.63   273.5  823.37   374.7  824.12   425.4  821.04
   445.7  817.37   455.7  816.18   465.7  817.26     476  822.32   516.5  848.59
   526.6  849.49     596  893.11   615.8   908.4   625.7  910.36   635.6  917.02
   675.2  955.34   704.8   980.2   714.7  987.51   734.5   994.3   823.5 1057.52
#Mann= 3 , 0 , 0
       0      .1       0   445.7    .045       0   465.7      .1       0
Bank Sta=445.7,465.7
XS Rating Curve= 0 ,0
Exp/Cntr=0.3,0.1

Type RM Length L Ch R = 1 ,1154    ,580.7,581.1,581.5
XS GIS Cut Line= 4
     1601202.358      339605.332     1601198.202      339224.438
     1601332.972      339039.414     1601292.205       338656.61
#Sta/Elev= 30
      10 1002.75    50.1  988.01    80.2  969.59   130.3  935.59   150.4  929.42
   200.5  899.42   230.6  885.89   250.6  880.89   280.7     864   320.8   834.8
   330.8  829.17   340.8  827.23   380.9  826.67   430.7  823.23   490.3  814.01
   500.3  812.81   510.3  814.28   560.1  830.78     580  833.69   670.6  871.04
   690.9  875.06   771.9  908.75   792.2   913.5   822.6  929.06   883.4  963.63
   893.5  967.46   903.6  969.15     934   984.7   964.4  998.15   994.8 1006.21
#Mann= 3 , 0 , 0
       0     .06       0   490.3    .045       0   510.3     .08       0
Bank Sta=490.3,510.3
XS Rating Curve= 0 ,0
Exp/Cntr=0.3,0.1

Type RM Length L Ch R = 1 ,572.9   ,287,293.5,299.9
XS GIS Cut Line= 4
      1601516.06      339718.021     1601701.845      339510.916
     1601840.423      339328.177     1601960.726      339011.429
#Sta/Elev= 30
     9.9 1010.36    49.7  983.67   129.2  942.99   139.1  940.36   228.5  889.74
   238.5  881.89   248.4  872.12   268.3  864.65   318.1  826.18   328.1  820.22
     348  812.59     358  809.68   367.9  808.75   377.9  808.72   387.9  808.96
   457.7  812.36   467.7  814.76   477.7  818.37   497.6  822.28   547.4  842.65
   587.3  861.31   597.3  864.56   607.2  865.84   637.1  878.36   696.9  905.74
   716.8  910.95   746.7  928.65   796.6  954.82   816.5  962.01   846.4  981.21
#Mann= 3 , 0 , 0
       0     .06       0   367.9    .045       0   387.9     .08       0
Bank Sta=367.9,387.9
XS Rating Curve= 0 ,0
Exp/Cntr=0.3,0.1

Type RM Length L Ch R = 1 ,279.4   ,38.2,38,37.8
XS GIS Cut Line= 4
     1601538.376      339703.415     1601954.679      339645.167
     1602025.776      339596.341      1602167.97      339288.825
#Sta/Elev= 30
      10  994.31    70.1     972    90.1  959.13   140.1  936.34   160.1  923.12
   170.1  918.74   210.2  903.55   230.2  894.16   250.2  888.71   260.2   884.8
   290.2  867.43   300.3  859.71   310.3  847.99   350.3  820.33   360.3  814.41
   370.3  811.77   380.3  811.06   420.4  810.36   448.7  803.84   458.7  803.45
   468.7  804.85     497  809.26   616.2  809.47   636.1  813.02   646.1  813.48
   745.8  867.61   755.7  867.94   765.7  872.87   825.5  905.81   845.4  919.03
#Mann= 3 , 0 , 0
      10     .06       0   448.7    .045       0   468.7     .06       0
#XS Ineff= 2 , 0
       0                     506       0
Permanent Ineff=
       F       F
Bank Sta=448.7,468.7
XS Rating Curve= 0 ,0
Exp/Cntr=0.3,0.1

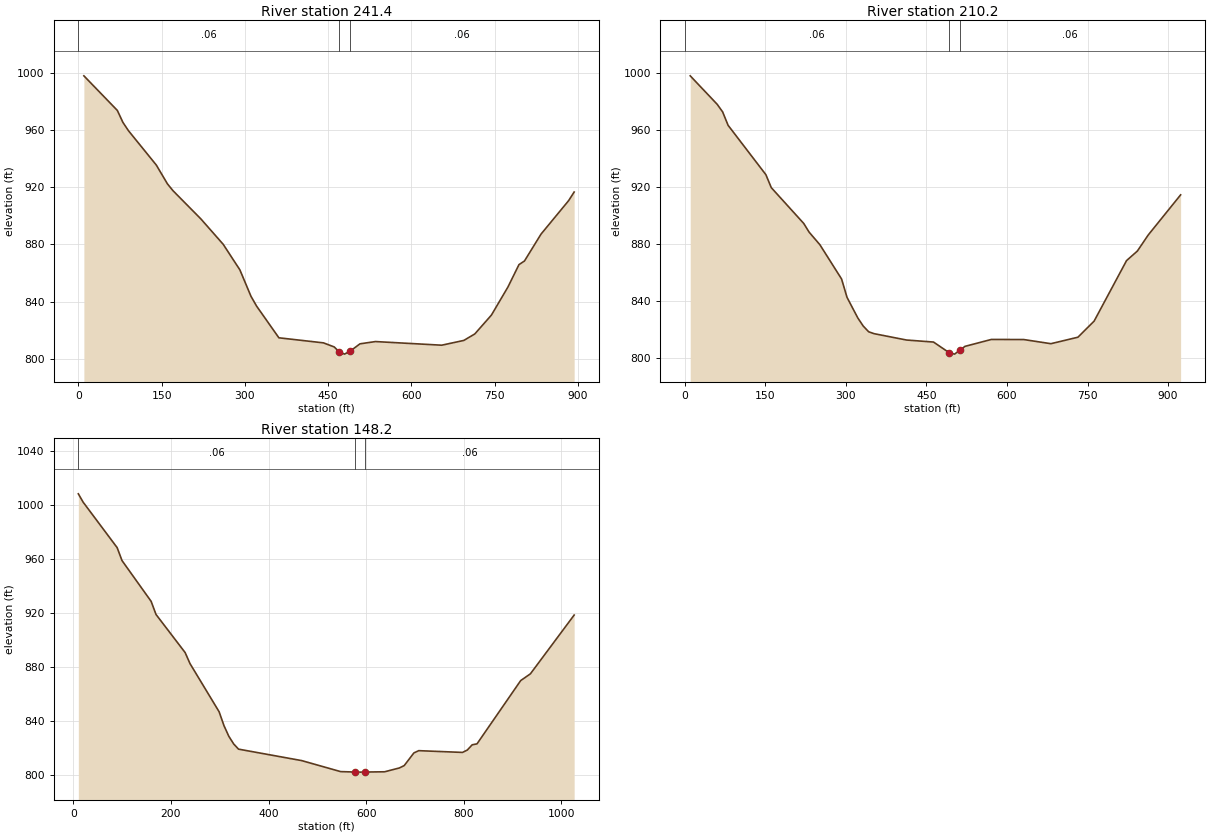
Type RM Length L Ch R = 1 ,241.4   ,31.4,31.2,30.9
XS GIS Cut Line= 4
     1601539.232      339711.125     1601988.728       339667.09
     1602057.148      339618.907     1602219.366      339299.961
#Sta/Elev= 30
      10  997.76    70.3  973.56    80.3  965.23    90.3  959.41   140.5  935.39
   160.6  922.22   170.6  917.45   220.8  897.74     261     880   291.1   862.1
   311.1  843.61   321.2  836.79   361.3  814.67   441.6  811.13   460.9  808.29
   469.5  805.02   479.5  803.26   489.5   805.3   507.4  810.46   535.3  812.04
   654.6   809.5   694.4  812.83   714.2  817.36   744.1  830.52   773.9  850.15
   793.8  865.81   803.7  868.35   833.5  887.13   883.2   910.5   893.2  916.55
#Mann= 3 , 0 , 0
       0     .06       0   469.5    .045       0   489.5     .06       0
Bank Sta=469.5,489.5
XS Rating Curve= 0 ,0
Exp/Cntr=0.3,0.1

Type RM Length L Ch R = 1 ,210.2   ,64.4,62,59.7
XS GIS Cut Line= 4
     1601542.087      339718.691     1602014.266      339686.364
     1602077.171      339640.884     1602234.784      339303.387
#Sta/Elev= 30
    10.1  997.97    60.4  977.99    70.5  972.67    80.6  963.33     151  928.72
   161.1  919.62   221.5  894.55   231.6  888.42   251.7  879.59     292  855.62
   302.1  842.79   322.2  828.35   332.3  822.68   342.4  818.66   352.4  817.34
   412.9  812.88   463.2  811.46   492.4     804   502.4     803   512.4  805.82
   521.8  808.44     571  813.29   631.4  813.21   681.8  810.31   732.1  814.84
   762.3  826.13   822.7  868.52   842.9  875.24     863  886.43   923.4  914.58
#Mann= 3 , 0 , 0
       0     .06       0   492.4    .045       0   512.4     .06       0
Bank Sta=492.4,512.4
XS Rating Curve= 0 ,0
Exp/Cntr=0.3,0.1

Type RM Length L Ch R = 1 ,148.2   ,147.9,148.2,148.5
XS GIS Cut Line= 4
     1601532.811       339733.25     1602040.338      339749.671
     1602166.257      339634.888     1602252.487      339297.248
#Sta/Elev= 30
      10 1008.61    19.9 1002.42    89.6  968.74    99.6  959.14   159.3  928.94
   169.3  919.24     229  891.01     239  882.84   298.7  847.14   308.7  836.83
   318.6  828.98   328.6  823.29   338.5  819.46     468  810.97   547.9  802.81
     578   802.5  588.07  802.43     598   802.5   638.1  802.68   668.2  805.51
   678.2  807.27   698.1  816.66     708  818.33   797.7  817.03   807.6   818.8
   817.6  822.67   827.5  823.38   917.1  870.26     937  875.26  1026.7   918.8
#Mann= 3 , 0 , 0
      10     .06       0     578    .045       0     598     .06       0
#XS Ineff= 2 , 0
       0     557             638       0
Permanent Ineff=
       F       F
Bank Sta=578,598
XS Rating Curve= 0 ,0
Exp/Cntr=0.3,0.1
Stream Node=brdncrk         ,Main            , 0 , 0 ,Upstream end
Stream Node=brdncrk         ,Main            , 0 , 1 ,Downstream end

Chan Stop Cuts=-1
Use User Specified Reach Order=0